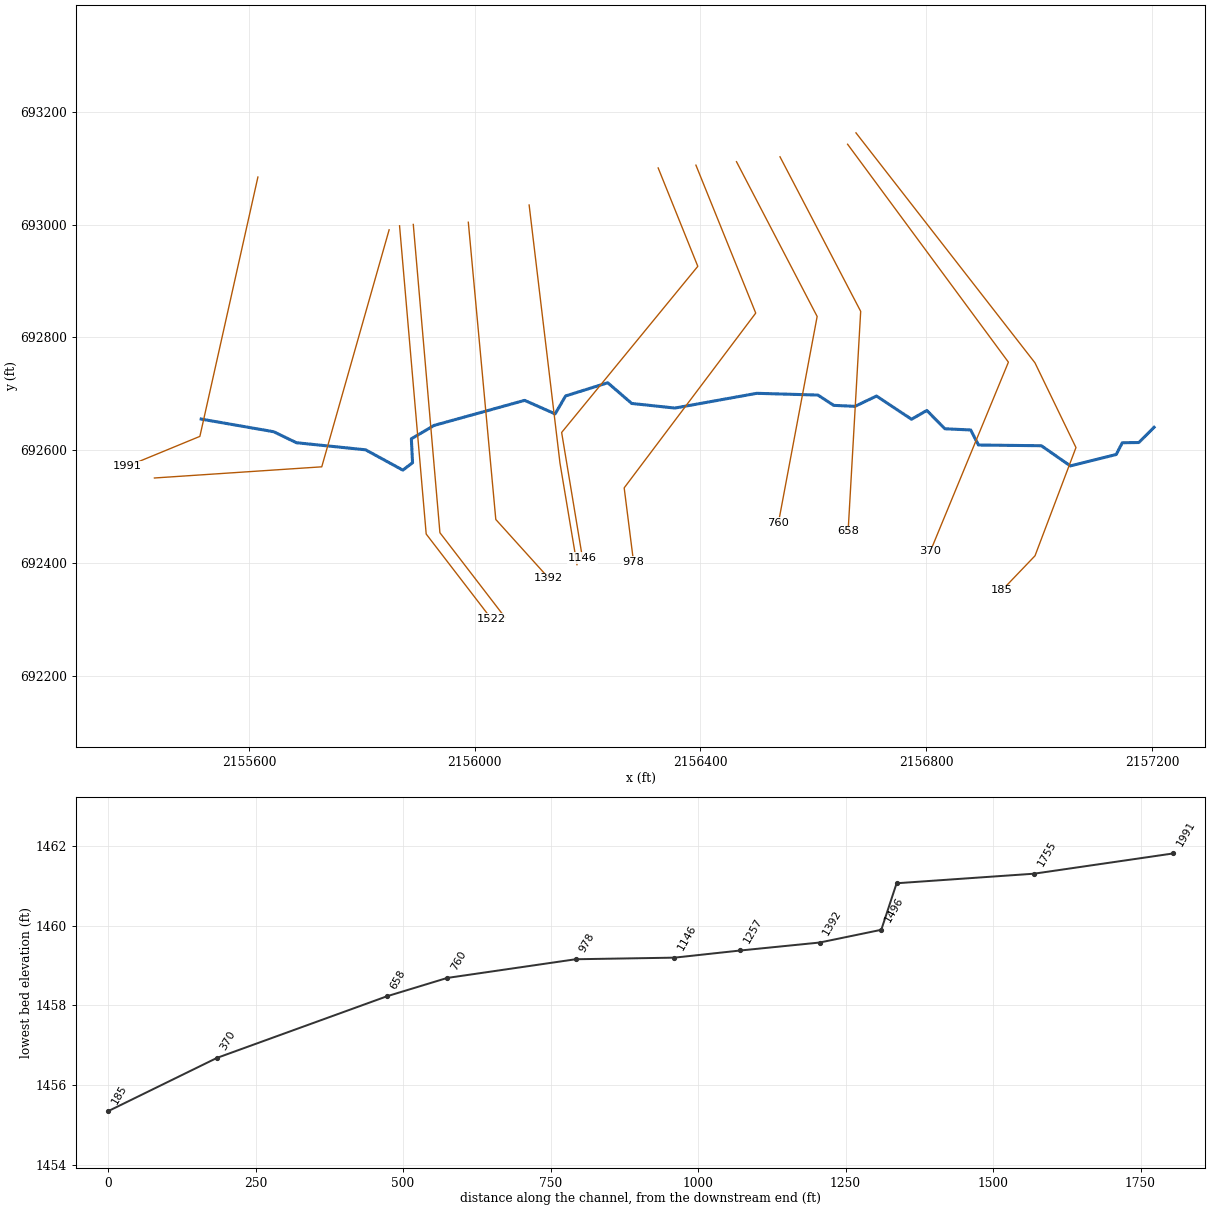
--- SLABCPFKT2.prj (project) ---

Proj Title=SLABCPFKT2
Current Plan=p01
Default Exp/Contr=0,0
English Units
Geom File=g01
Flow File=f01
Plan File=p01
BEGIN DESCRIPTION:
---------- MODELED AS PART OF WVEMD CTP PROGRAM, 2023----------
Stream Name: Slab Camp Fork Tributary 2
Flood Zone:  AFH
Upshur County, WV
HEC-RAS Version: RAS 6.3
Vertical Datum: NAVD88
Projection: NAD 1983 StatePlane West Virginia S FIPS 4702 (US Feet)
Terrain: 1-meter LIDAR (FEMA Region III 3DEP collected 2016-2018)
Land Use: 2019 NLCD
Hydrologic Method:
WV SIR2010-5033 regression equations
Additional Model Notes:
Main stem is SLABCMPFK; qualifies for coincident peak modeling, but normal depth boundary condition achieves tie-in
END DESCRIPTION:
DSS Export Rating Curves= 0
DSS Export Rating Curve Sorted= 0
DSS Export Volume Flow Curves= 0
DXF OffsetX= 0
DXF OffsetY= 0
DXF ScaleX= 0
DXF ScaleY= 0

--- SLABCPFKT2.p01 (plan) ---

Plan Title=Floodplain
Program Version=6.31
Short Identifier=Floodplain
Geom File=g01
Flow File=f01
Subcritical Flow
K Sum by GR= 0
Std Step Tol= 0.01
Critical Tol= 0.01
Num of Std Step Trials= 20
Max Error Tol= 0.3
Flow Tol Ratio= 0.001
Split Flow NTrial= 30
Split Flow Tol= 0.02
Split Flow Ratio= 0.02
Log Output Level= 0
Friction Slope Method= 1
Unsteady Friction Slope Method= 2
Unsteady Bridges Friction Slope Method= 1
Parabolic Critical Depth
Global Vel Dist= 0 , 0 , 0
Global Log Level= 0
CheckData=True
Encroach Param=-1 ,0,0, 0
Mapping Interval=1HOUR
Computation Time Step Use Courant=        0
Computation Time Step Use Time Series=    0
Computation Time Step Count To Double=0
Computation Time Step Max Doubling=0
Computation Time Step Max Halving=0
Computation Time Step Residence Courant=0
Run HTab= 0
Run UNet= 0
Run Sediment= 0
Run PostProcess= 0
Run WQNet= 0
Run RASMapper=-1
UNET Theta= 0
UNET Theta Warmup= 0
UNET ZTol= 0
UNET ZSATol= 0
UNET MxIter= 0
UNET Max Iter WO Improvement= 0
UNET MaxInSteps= 0
UNET DtIC= 0
UNET DtMin= 0
UNET MaxCRTS= 0
UNET WFStab= 0
UNET SFStab= 0
UNET WFX= 1
UNET SFX= 1
UNET Gravity=32.17405
UNET 1D Methodology=Finite Difference
UNET DSS MLevel= 1
UNET Pardiso=0
UNET DZMax Abort= 0
UNET Use Existing IB Tables= 0
UNET Froude Reduction=False
UNET Froude Limit= 0
UNET Froude Power= 0
UNET D1 Cores= 0
UNET WindReference=Eulerian
UNET WindDragFormulation=Hsu (1988)
UNET D2 Coriolis=0
UNET D2 Cores= 0
UNET D2 Theta= 1
UNET D2 Theta Warmup= 1
UNET D2 Z Tol= 0.01
UNET D2 Volume Tol= 0.01
UNET D2 Max Iterations= 20
UNET D2 Equation= 0
UNET D2 RampUpFraction=0.1
UNET D2 TimeSlices= 1
UNET D2 Turbulence Formulation=Non-Conservative (original)
UNET D2 Eddy Viscosity=0.3
UNET D2 Transverse Eddy Viscosity=0.1
UNET D2 Smagorinsky Mixing=0
UNET D2 BCVolumeCheck=0
UNET D2 Cores=0
UNET D2 SolverType=PARDISO (Direct)
UNET D2 Minimum Iterations= 3
UNET D2 Maximum Iterations= 30
UNET D2 Restart Number= 10
UNET D2 Relaxation Coeff=1.3
UNET D2 SOR Precondition Iterations= 10
UNET D2 ILUT Maximum Fill= 8
UNET D2 ILUT Tolerance=1E-08
UNET D2 Convergence Tolerance=0.00001
UNET D1D2 MaxIter= 0
UNET D1D2 ZTol=0.01
UNET D1D2 QTol=0.1
UNET D1D2 MinQTol=1
Write IC File= 0
Write IC File at Fixed DateTime=0
Write IC File at Sim End=0
Echo Input=False
Echo Parameters=False
Echo Output=False
Write Detailed= 0
HDF Write Warmup=0
HDF Write Time Slices=0
HDF Flush=0
HDF Compression= 1
HDF Chunk Size= 1
HDF Spatial Parts= 1
HDF Use Max Rows=0
HDF Fixed Rows= 1
Calibration Method= 0
Calibration Iterations= 20
Calibration Max Change=0.05
Calibration Tolerance=0.2
Calibration Maximum=1.5
Calibration Minimum=0.5
Calibration Optimization Method= 1
WQ AD Non Conservative
WQ ULTIMATE=-1
WQ Max Comp Step=1HOUR
WQ Output Interval=15MIN
WQ Output Selected Increments= 0
WQ Create Restart=0
WQ Fixed Restart=0
WQ System Summary=0
WQ Write To DSS=0
Sorting and Armoring Iterations= 10
XS Update Threshold= 0.02
Bed Roughness Predictor= 0
Hydraulics Update Threshold= 0.02
Energy Slope Method= 1
Volume Change Method= 1
Sediment Retention Method= 0
Sediment TS Multiplier= 1
Warm Up Method= 0
XS Weighting Method= 0
Number of US Weighted Cross Sections= 1
Number of DS Weighted Cross Sections= 1
Upstream XS Weight=0
Main XS Weight=1
Downstream XS Weight=0
Number of DS XS's Weighted with US Boundary= 1
Upstream Boundary Weight= 1
Weight of XSs Associated with US Boundary= 0
Number of US XS's Weighted with DS Boundary= 1
Downstream Boundary Weight= 0.5
Weight of XSs Associated with DS Boundary= 0.5
Percentile Method= 0
Sediment Output Level= 3
Mass or Volume Output= 0
Output Increment Type= 1
Profile and TS Output Increment= 1
Transport Output Increment 1
XS Output Flag= 0
XS Output Increment= 10
Read HDF5 Sediment Hotstart= 0
Sediment Hotstart Type= 0
Write Gradation File= 0
Read Gradation Hotstart= 0
Write HDF5 File= 1
Write Binary Output= 1
Write DSS Sediment File= 0
DSS Sediment Output Type= 1
SV Curve= 0
Specific Gage Flag= 0
Subcell Erosion Methods= 0
Subcell Deposition Methods= 0
Advection Scheme= 1
Matrix Solver= 0
Implicit Weighting Factor= 1
Maximum Outer Loop Convergence Iterations= 5
Convergence Maximum Absolute= 0.001
Convergence RMSE= 0.0001
Grain Fractions Max Abs Error= 0.001
Max Subgrid Regions= 1
Max Subgrid Length Scale= 3.402823E+38
Initial Layer Thickness= 3.402823E+38
Min Layer Thickness= 3.402823E+38
Max Layer Thickness= 3.402823E+38
Number of Layers= 5

--- SLABCPFKT2.f01 (steady flow) ---

Flow Title=Flows
Program Version=6.31
Number of Profiles= 1
Profile Names=01pct
River Rch & RM=SLABCPFKT2,Main,1991
     341
Boundary for River Rch & Prof#=SLABCPFKT2,Main            , 1
Up Type= 0
Dn Type= 3
Dn Slope=0.00675
DSS Import GetInterval= 0
DSS Import GetPeak= 0
DSS Import FillOption= 0

--- SLABCPFKT2.g01 (geometry) ---

Geom Title=Geometry
Program Version=6.31

River Reach=SLABCPFKT2      ,Main
Reach XY= 30
2155515.29603478692655.322758531     2155643.762 692632.92095036
     2155684.082      692613.4192155806.59849659692600.890412982
     2155872.636      692564.885     2155889.806      692577.963
2155887.70208273692620.3869172662155928.17510015692644.135782035
     2156088.403      692688.5082156142.49806124692664.534541022
      2156161.06       692696.322156235.76391727692719.684148922
2156278.21780437692683.0294158372156354.64515471692674.869912242
2156499.89295036 692700.99904964     2156608.163      692697.894
     2156636.207      692679.637     2156673.809       692677.92
      2156712.04      692696.1492156774.03618202692655.038347484
2156801.22298345692670.580917266     2156833.231      692638.143
     2156878.845      692636.054     2156892.753      692609.355
     2157004.185      692608.0962157055.46593381692572.368082734
2157136.75004964692592.543049641     2157147.582       692613.39
     2157176.799      692613.791     2157203.899      692640.776

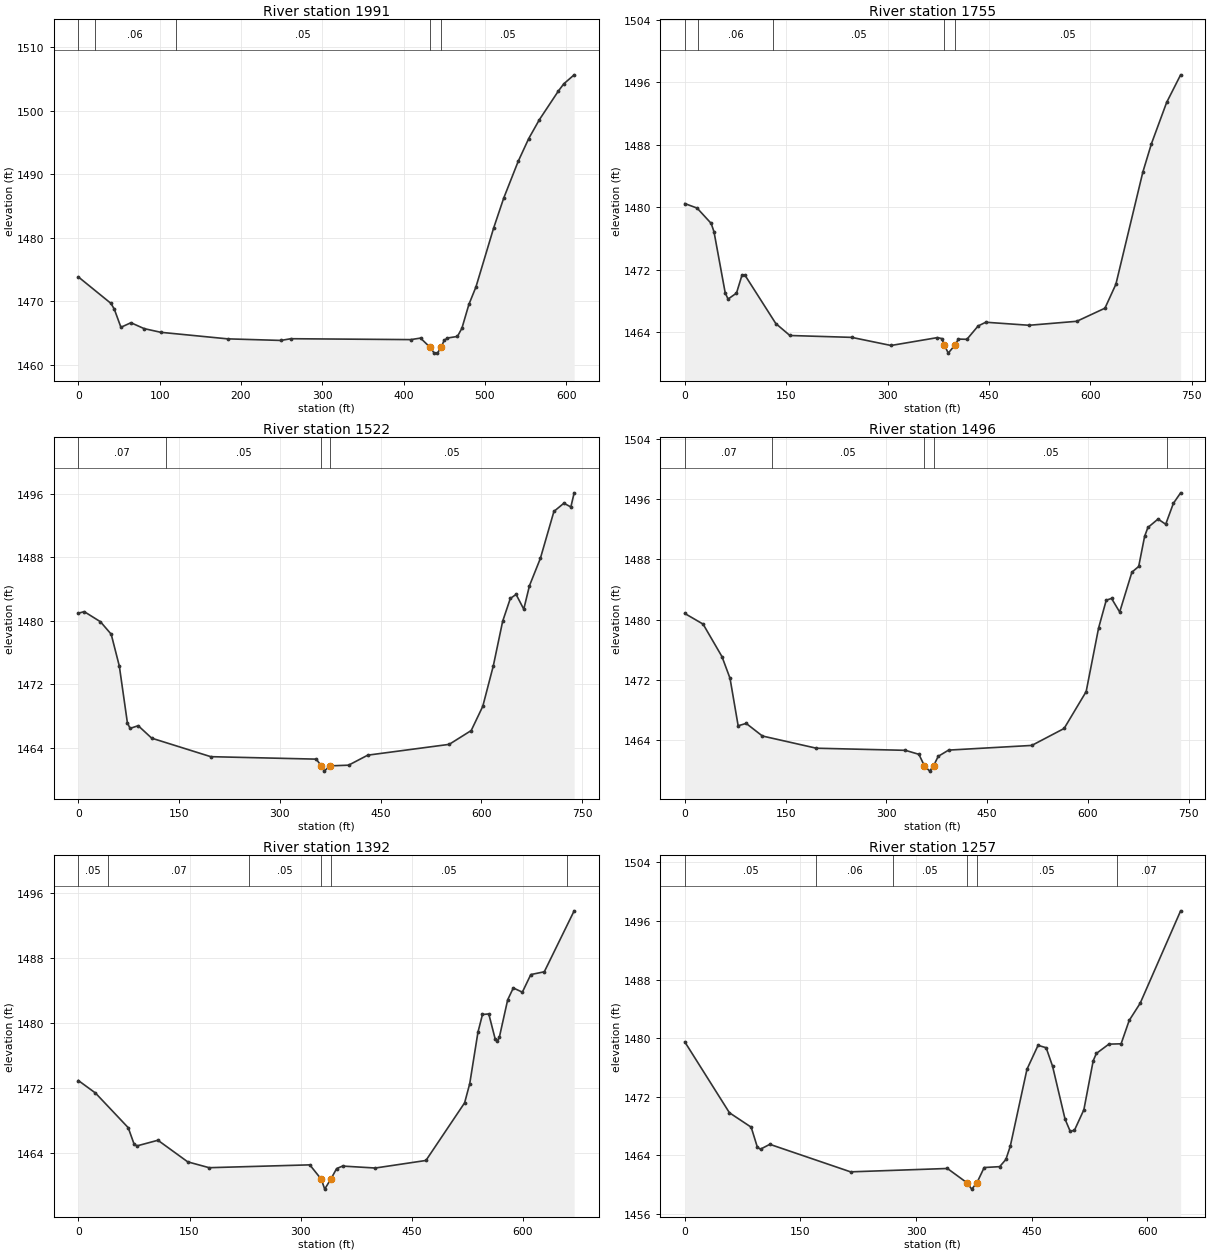
Type RM Length L Ch R = 1 ,1991    ,236.3,236.3,236.3
XS GIS Cut Line= 3
2155615.77579592693084.2731832572155512.94244697692624.692676278
 2155384.4596665  692571.7478963
#Sta/Elev= 30
       0 1473.83    40.1 1469.66    44.2 1468.76    52.4 1465.89    64.7 1466.61
      81 1465.68   101.5  1465.1   183.5 1464.07   249.1 1463.82   261.4 1464.09
     409 1463.95   420.9 1464.19432.62451462.743   437.6 1461.86   441.8 1461.82
     446 1462.73     450 1463.81   454.1  1464.2   466.3 1464.45   471.8 1465.73
   480.4 1469.49   489.1 1472.25   510.7 1481.47   523.2 1486.23     541 1492.02
   553.9  1495.6     567 1498.58   590.6 1503.14   597.2 1504.26   609.9 1505.67
#Mann= 5 ,-1,0
       0     .05       0      20     .06       0     120     .05       0
432.6245    .045       0     446     .05       0
Bank Sta=432.6245,446
XS Rating Curve= 0 ,0
Exp/Cntr=0.3,0.1

Type RM Length L Ch R = 1 ,1755    ,222.5,232.9,232.6
XS GIS Cut Line= 3
2155848.30090757692990.7271515442155728.92719983692570.723162368
2155432.39744964692550.947657754
#Sta/Elev= 30
       0 1480.48    18.2  1479.9      39 1477.94    43.2 1476.87    59.8 1469.04
      64 1468.24    76.5    1469    84.8 1471.35    88.9 1471.32   134.7  1465.1
   155.5 1463.57     247 1463.33   305.2 1462.29   373.9  1463.3   380.2 1463.18
  384.03 1462.36   389.9 1461.31   399.8 1462.34     405 1463.11   417.5 1463.08
   434.1 1464.79   445.4 1465.27   509.6 1464.88   580.1 1465.39   621.8 1467.07
     638 1470.14   677.9 1484.52   690.6 1488.15   713.1 1493.44   733.8 1496.98
#Mann= 5 ,-1,0
       0     .07       0      20     .06       0     130     .05       0
  384.03    .045       0   399.8     .05       0
Bank Sta=384.03,399.8
XS Rating Curve= 0 ,0
Exp/Cntr=0.3,0.1

Type RM Length L Ch R = 1 ,1522    ,25.2,26,25.3
XS GIS Cut Line= 3
2155866.78455729 692997.927251852155913.99704411692451.608198576
2156029.52350401692301.305314475
#Sta/Elev= 30
       0 1480.95     8.8 1481.15    32.9 1479.88    48.9 1478.31      61  1474.3
      73 1467.16      77 1466.45    89.1 1466.79   109.2 1465.22   197.1 1462.89
   354.1 1462.58  361.64 1461.73   366.1 1461.07   374.1 1461.73   402.2 1461.82
   430.7 1463.08   551.9 1464.44   584.7 1466.18   601.9 1469.23   617.6 1474.33
   631.5 1479.94   642.9 1482.81   651.5 1483.32   662.9 1481.46   671.4 1484.42
   687.6 1487.85   707.8 1493.77   722.6  1494.8     733 1494.33   737.9 1496.11
#Mann= 4 ,-1,0
       0     .07       0     130     .05       0  361.64    .045       0
   374.1     .05       0
Bank Sta=361.64,374.1
XS Rating Curve= 0 ,0
Exp/Cntr=0.3,0.1

Type RM Length L Ch R = 1 ,1496    ,103.7,104.4,104.4
XS GIS Cut Line= 3
2155891.12341259693000.2731620312155938.33589942692453.954108757
2156053.86235932692303.651224656
#Sta/Elev= 30
       0 1480.82    27.2 1479.41    55.3  1475.1    67.3 1472.22    79.4 1465.92
    91.4 1466.23   115.5 1464.56   195.8 1462.94   328.3 1462.66   348.4 1462.13
   356.4 1460.64   364.4  1459.9  370.36 1460.63   377.1 1461.86   392.6 1462.69
   516.4 1463.31   564.5 1465.56   597.3 1470.45   615.8 1478.88   627.2 1482.58
   635.1 1482.82   647.2 1481.01   665.4  1486.3   675.5 1487.06   684.3 1491.05
   689.2 1492.23   704.3 1493.35   715.7 1492.66   727.1 1495.43   737.9 1496.83
#Mann= 5 ,-1,0
       0     .07       0     130     .05       0   356.4    .045       0
  370.36     .05       0  718.36      .1       0
Bank Sta=356.4,370.36
XS Rating Curve= 0 ,0
Exp/Cntr=0.3,0.1

Type RM Length L Ch R = 1 ,1392    ,131.9,134.4,132.7
XS GIS Cut Line= 3
2155988.64210729693004.1719566592156037.36658272692477.396024151
2156131.13821469 692373.51176521
#Sta/Elev= 30
       0 1472.96    23.1 1471.42    67.3 1467.15    75.3 1465.11    79.3 1464.91
   107.4  1465.6   147.6 1462.94   176.5 1462.22   312.3 1462.57  327.89 1460.79
   332.4 1459.58   340.61460.799   348.5 1462.11   356.5 1462.42   400.7 1462.18
     469 1463.11   521.2 1470.21   528.1 1472.57   539.2 1478.91   545.3 1481.09
   553.8 1481.16   562.3 1478.12   565.2 1477.81     568 1478.26   579.3  1482.9
   586.9 1484.36   599.1 1483.84   610.5 1486.01   628.7 1486.35     669 1493.86
#Mann= 6 ,-1,0
       0     .05       0      40     .07       0     230     .05       0
  327.89    .045       0   340.6     .05       0  659.02      .1       0
Bank Sta=327.89,340.6
XS Rating Curve= 0 ,0
Exp/Cntr(USF)=0,0
Exp/Cntr=0.3,0.1

Type RM Length L Ch R = 1 ,1257    ,119.8,111.7,87
XS GIS Cut Line= 3
 2156096.4268467693034.7096378612156151.08287178692577.351028491
 2156181.2142522692397.378458771
#Sta/Elev= 30
       0 1479.49    57.9 1469.81    86.1 1467.84    94.2 1465.08    98.2 1464.84
   110.3  1465.5     215 1461.74   340.6  1462.2  365.58 1460.28   372.2 1459.38
     379 1460.27   388.3 1462.33   408.4 1462.45   416.5 1463.44   422.2 1465.26
   443.8 1475.75   458.2 1479.02   468.7 1478.69     477 1476.17   493.2 1468.94
   499.9 1467.27   505.4 1467.42   517.6 1470.22   529.7 1476.91   533.8 1477.91
     550 1479.18   565.9 1479.23   576.4 1482.42   590.6 1484.76   643.1 1497.39
#Mann= 6 ,-1,0
       0     .05       0     170     .06       0     270     .05       0
  365.58    .045       0     379     .05       0  560.61     .07       0
Bank Sta=365.58,379
XS Rating Curve= 0 ,0
Exp/Cntr=0.3,0.1

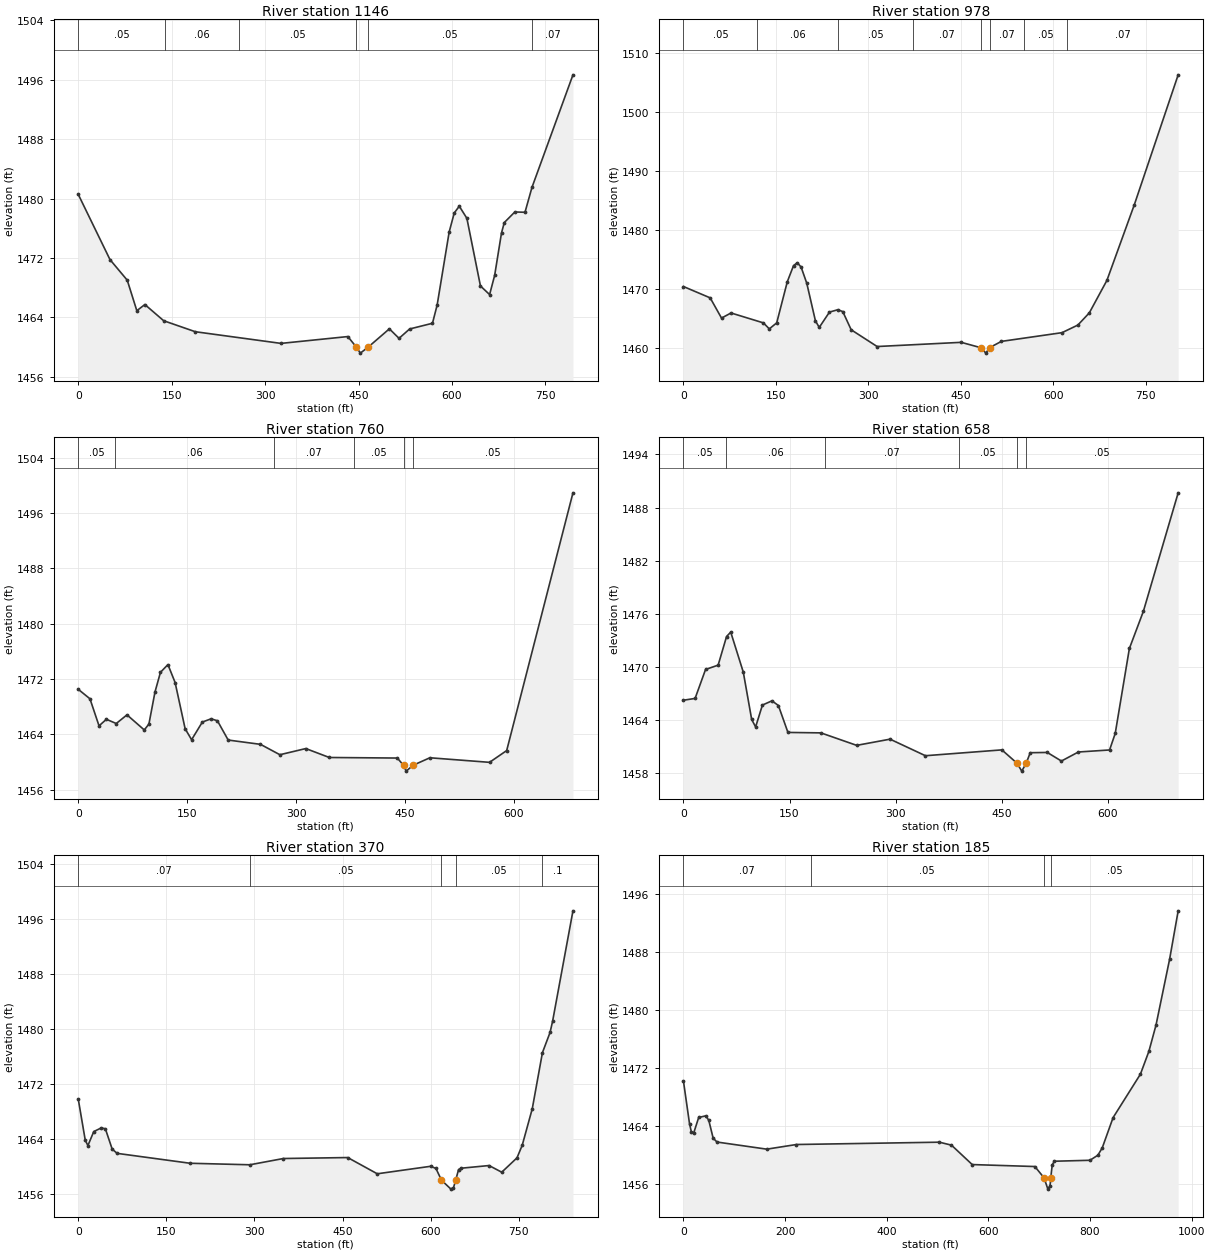
Type RM Length L Ch R = 1 ,1146    ,162.8,167.3,178.7
XS GIS Cut Line= 4
2156325.10063008693100.367618036  2156395.329306692926.031784856
2156154.03398589692631.6213106212156190.94642849692409.195712851
#Sta/Elev= 30
       0 1480.56    50.9 1471.79    78.6 1469.02      94 1464.91   106.9 1465.74
   137.1 1463.56   187.9 1462.08   325.4 1460.51   432.7 1461.43   446.41460.009
   452.8  1459.2   465.4 1460.01   499.4 1462.47   514.9 1461.19   531.9 1462.45
   568.6 1463.22   576.1 1465.68   595.4 1475.51   603.5 1478.06   611.6 1478.98
   623.8 1477.35   645.6 1468.24   660.3 1467.08   668.4 1469.67   679.4 1475.38
   683.9 1476.78   700.8  1478.2   717.1 1478.16   728.3 1481.51   794.1 1496.66
#Mann= 6 ,-1,0
       0     .05       0     140     .06       0  257.95     .05       0
   446.4    .045       0   465.4     .05       0  728.61     .07       0
Bank Sta=446.4,465.4
XS Rating Curve= 0 ,0
Exp/Cntr=0.3,0.1

Type RM Length L Ch R = 1 ,978     ,209.4,217.9,220.4
XS GIS Cut Line= 4
      2156391.99      693105.3452156497.97038745692843.162104195
2156264.84688712692533.4294678752156281.43192802 692402.52825163
#Sta/Elev= 30
       0 1470.45    43.3 1468.53    61.7  1465.1    77.1 1465.97   129.6 1464.29
   139.2 1463.27   151.2 1464.29   168.4 1471.27   178.5    1474   184.6 1474.49
   190.8 1473.75     200    1471     214 1464.64   220.2 1463.52   236.8 1466.12
   250.4 1466.52   258.4  1466.2     272 1463.12   314.1 1460.28   450.5 1460.99
   482.6 1460.07   490.5 1459.16  496.55 1460.09   515.6 1461.15     614 1462.63
   639.7 1463.92   658.3 1465.99   686.8 1471.49   731.2  1484.3   802.4 1506.35
#Mann= 8 ,-1,0
       0     .05       0     120     .06       0     250     .05       0
  372.79     .07       0   482.6    .045       0  496.55     .07       0
  552.79     .05       0  622.79     .07       0
Bank Sta=482.6,496.55
XS Rating Curve= 0 ,0
Exp/Cntr=0.3,0.1

Type RM Length L Ch R = 1 ,760     ,99.1,102,101.7
XS GIS Cut Line= 3
 2156463.8794242693111.4543423072156606.82122528692837.155891189
2156538.19613517692471.399332391
#Sta/Elev= 30
       0 1470.51    16.1 1469.14    28.6 1465.23    38.7 1466.18    52.3 1465.57
    67.1 1466.82    90.9 1464.64    97.3 1465.49   105.7 1470.14   113.2 1472.97
   123.5 1474.08   133.4 1471.49   147.2 1464.81   156.1 1463.23   170.9 1465.78
     183 1466.25   191.7 1465.96   206.5 1463.18     251 1462.56   277.7 1461.06
   313.4 1461.95   345.8 1460.66   439.5 1460.58  447.98 1459.53   451.7 1458.69
   461.21459.538   484.3 1460.62   566.5 1459.96   590.1 1461.66   681.4  1498.9
#Mann= 6 ,-1,0
       0     .05       0      50     .06       0     270     .07       0
  379.31     .05       0  447.98    .045       0   461.2     .05       0
Bank Sta=447.98,461.2
XS Rating Curve= 0 ,0
Exp/Cntr=0.3,0.1

Type RM Length L Ch R = 1 ,658     ,272,288.3,264.2
XS GIS Cut Line= 3
2156540.99499363  693120.11712262156683.96083111 692846.25399237
2156661.68044085692456.347162889
#Sta/Elev= 30
       0 1466.24    16.4 1466.44    31.2 1469.71      49  1470.2    60.9 1473.43
    66.8 1473.93    84.6  1469.4    96.4 1464.07     102 1463.22   111.6 1465.69
   125.1 1466.17   134.2 1465.64   147.7  1462.6   194.3 1462.55   244.9 1461.14
   292.1 1461.84   342.1 1459.97   450.2 1460.63   471.8 1459.11   478.3 1458.23
   484.5  1459.1   490.3 1460.31   514.4 1460.34   534.4 1459.37   558.4 1460.39
   602.5 1460.62   610.5 1462.49   630.5 1472.08   650.3 1476.28   699.5 1489.66
#Mann= 6 ,-1,0
       0     .05       0      60     .06       0     200     .07       0
  388.93     .05       0   471.8    .045       0   484.5     .05       0
Bank Sta=471.8,484.5
XS Rating Curve= 0 ,0
Exp/Cntr(USF)=0,0
Exp/Cntr=0.3,0.1

Type RM Length L Ch R = 1 ,370     ,177.9,184.6,180.1
XS GIS Cut Line= 3
2156660.75209126693142.3975128562156945.75541662692756.204081751
2156807.43132711692421.069878317
#Sta/Elev= 30
       0 1469.75    11.9 1463.79    16.4 1463.01    26.4 1465.05    39.4 1465.59
    46.2 1465.44    57.7 1462.51    66.1 1461.88   190.4 1460.44   292.2 1460.22
   349.3 1461.13   458.9 1461.27   509.2 1458.91   600.1    1460   609.1 1459.69
   618.61457.979   634.7 1456.68     639 1456.88   642.8 1457.99   647.7 1459.53
     652 1459.72   699.6 1460.11   721.2 1459.14   747.2 1461.23   756.1 1463.06
   773.2 1468.37   790.5 1476.52   803.5 1479.46   807.8 1481.08   842.5 1497.14
#Mann= 5 ,-1,0
       0     .07       0   292.2     .05       0   618.6    .045       0
   642.8     .05       0   790.5      .1       0
Bank Sta=618.6,642.8
XS Rating Curve= 0 ,0
Exp/Cntr(USF)=0,0
Exp/Cntr=0.3,0.1

Type RM Length L Ch R = 1 ,185     ,,,
XS GIS Cut Line= 5
2156675.62096677693162.5660065362156992.78030903692755.088108685
2157065.47662653 692604.890055812156992.88508437692413.052781821
2156934.01297909692351.566146517
#Sta/Elev= 30
       0 1470.17    11.9 1464.33    15.6 1463.18    20.4 1463.13    29.9  1465.2
    44.1 1465.43    49.8  1464.8    58.4 1462.35      66 1461.82   163.9 1460.84
   222.3 1461.48   503.6  1461.8   527.4 1461.39   568.2 1458.72   691.5 1458.45
   709.5  1456.9   717.1 1455.34   721.4 1455.83  722.77 1456.91   725.7  1458.7
     730 1459.18   799.9 1459.31   815.5 1460.01   824.1 1461.02   845.4 1465.18
   899.2 1471.16   915.9 1474.31   929.9 1477.92   956.7    1487   973.5 1493.64
#Mann= 4 ,-1,0
       0     .07       0     250     .05       0   709.5    .045       0
  722.77     .05       0
Bank Sta=709.5,722.77
XS Rating Curve= 0 ,0
Exp/Cntr=0.3,0.1
LCMann Table=0

Chan Stop Cuts=-1
Use User Specified Reach Order=0
Composite Channel Slope=5